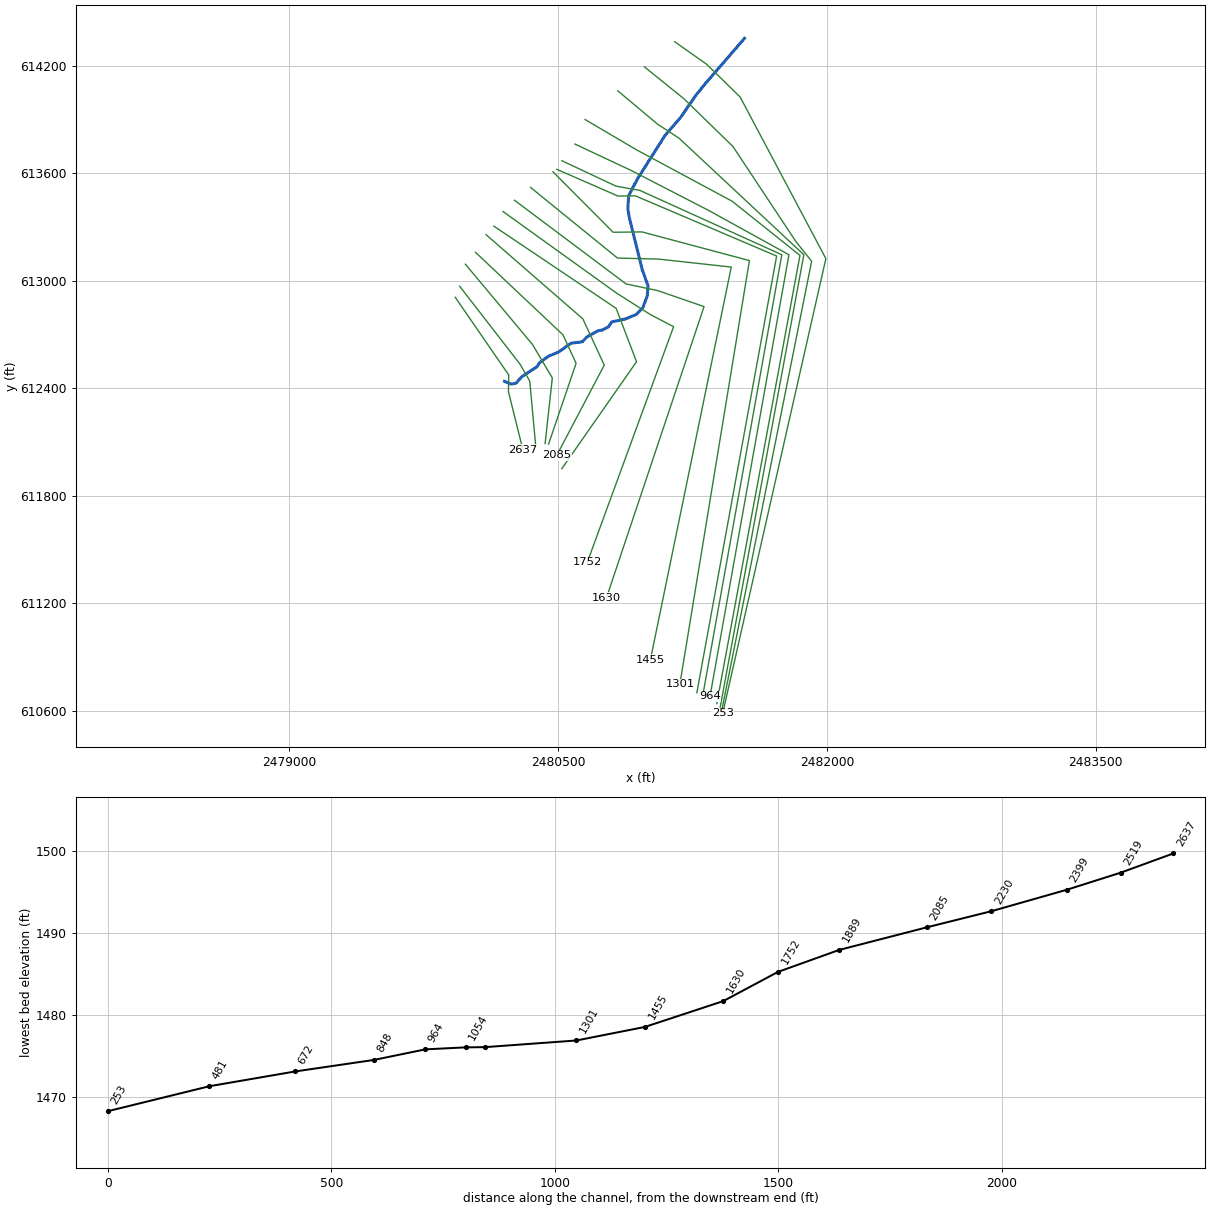
--- SFSBPOTOMC_T3.prj (project) ---

Proj Title=SFSBPOTOMC_T3
Current Plan=p01
Default Exp/Contr=0,0
English Units
Geom File=g01
Flow File=f01
Plan File=p01
BEGIN DESCRIPTION:
Stream Name: South Fork South Branch Potomac River Tributary 3
Flood Zone: Zone A
Pendleton County, WV
WVDHSEM Flood Warning & Analysis Mapping
HEC-RAS Version: 5.0.7
Hydrology Method:
Regression
Model Notes:
Tie in with SFSBPOTOMC at the downstream end.
END DESCRIPTION:
DSS Export Rating Curves= 0
DSS Export Rating Curve Sorted= 0
DSS Export Volume Flow Curves= 0
DXF OffsetX= 0
DXF OffsetY= 0
DXF ScaleX= 0
DXF ScaleY= 0

--- SFSBPOTOMC_T3.p01 (plan) ---

Plan Title=Floodplain
Program Version=5.07
Short Identifier=Floodplain
Geom File=g01
Flow File=f01
Subcritical Flow
K Sum by GR= 0
Std Step Tol= 0.01
Critical Tol= 0.01
Num of Std Step Trials= 20
Max Error Tol= 0.3
Flow Tol Ratio= 0.001
Split Flow NTrial= 30
Split Flow Tol= 0.02
Split Flow Ratio= 0.02
Log Output Level= 0
Friction Slope Method= 1
Unsteady Friction Slope Method= 2
Unsteady Bridges Friction Slope Method= 1
Parabolic Critical Depth
Global Vel Dist= 0 , 0 , 0
Global Log Level= 0
CheckData=True
Encroach Param=-1 ,0,0, 0
Mapping Interval=1HOUR
Computation Time Step Use Courant=        0
Computation Time Step Use Time Series=    0
Computation Time Step Count To Double=0
Computation Time Step Max Doubling=0
Computation Time Step Max Halving=0
Computation Time Step Residence Courant=0
Run HTab= 0
Run UNet= 0
Run Sediment= 0
Run PostProcess= 0
Run WQNet= 0
Run RASMapper= 0
UNET Theta= 0
UNET Theta Warmup= 0
UNET ZTol= 0
UNET ZSATol= 0
UNET MxIter= 0
UNET Max Iter WO Improvement= 0
UNET MaxInSteps= 0
UNET DtIC= 0
UNET DtMin= 0
UNET MaxCRTS= 0
UNET WFStab= 0
UNET SFStab= 0
UNET WFX= 1
UNET SFX= 1
UNET 1D Methodology=Finite Difference
UNET DSS MLevel= 1
UNET Pardiso=0
UNET DZMax Abort= 0
UNET Use Existing IB Tables= 0
UNET Froude Reduction=False
UNET Froude Limit= 0
UNET Froude Power= 0
UNET D1 Cores= 0
UNET D2 Coriolis=0
UNET D2 Cores= 0
UNET D2 Theta= 1
UNET D2 Theta Warmup= 1
UNET D2 Z Tol= 0.01
UNET D2 Volume Tol= 0.01
UNET D2 Max Iterations= 20
UNET D2 Equation= 0
UNET D2 RampUpFraction=0.1
UNET D2 TimeSlices= 1
UNET D2 BCVolumeCheck=0
UNET D1D2 MaxIter= 0
UNET D1D2 ZTol=0.01
UNET D1D2 QTol=0.1
UNET D1D2 MinQTol=1
Write IC File= 0
Write IC File at Fixed DateTime=0
Write IC File at Sim End=0
Echo Input=False
Echo Parameters=False
Echo Output=False
Write Detailed= 0
HDF Write Warmup=0
HDF Write Time Slices=0
HDF Flush=0
HDF Face Node Velocities=0
HDF Compression= 1
HDF Chunk Size= 1
HDF Spatial Parts= 1
HDF Use Max Rows=0
HDF Fixed Rows= 1
Calibration Method= 0
Calibration Iterations= 20
Calibration Max Change=0.05
Calibration Tolerance=0.2
Calibration Maximum=1.5
Calibration Minimum=0.5
Calibration Optimization Method= 1
WQ AD Non Conservative
WQ ULTIMATE=-1
WQ Max Comp Step=1HOUR
WQ Output Interval=15MIN
WQ Output Selected Increments= 0
WQ Output face flow=0
WQ Output face velocity=0
WQ Output face area=0
WQ Output face dispersion=0
WQ Output cell volume=0
WQ Output cell surface area=0
WQ Output cell continuity=0
WQ Output cumulative cell continuity=0
WQ Output face conc=0
WQ Output face dconc_dx=0
WQ Output face courant=0
WQ Output face peclet=0
WQ Output face adv mass=0
WQ Output face disp mass=0
WQ Output cell mass=0
WQ Output cell source sink temp=0
WQ Output nsm pathways=0
WQ Output nsm derived pathways=0
WQ Output MaxMinRange=-1
WQ Daily Max Min Mean=-1
WQ Daily Range=0
WQ Daily Time=0
WQ Create Restart=0
WQ Fixed Restart=0
WQ System Summary=0
WQ Write To DSS=0
WQ Use Fixed Temperature=0
Sorting and Armoring Iterations= 10
XS Update Threshold= 0.02
Bed Roughness Predictor= 0
Hydraulics Update Threshold= 0.02
Energy Slope Method= 1
Volume Change Method= 1
Sediment Retention Method= 0
XS Weighting Method= 0
Number of US Weighted Cross Sections= 1
Number of DS Weighted Cross Sections= 1
Upstream XS Weight=0
Main XS Weight=1
Downstream XS Weight=0
Number of DS XS's Weighted with US Boundary= 1
Upstream Boundary Weight= 1
Weight of XSs Associated with US Boundary= 0
Number of US XS's Weighted with DS Boundary= 1
Downstream Boundary Weight= 0.5
Weight of XSs Associated with DS Boundary= 0.5
Percentile Method= 0
Sediment Output Level= 3
Mass or Volume Output= 0
Output Increment Type= 1
Profile and TS Output Increment= 1
XS Output Flag= 0
XS Output Increment= 10
Write Gradation File= 0
Read Gradation Hotstart= 0
Write HDF5 File= 1
Write Binary Output= 1
Write DSS Sediment File= 0
SV Curve= 0
Specific Gage Flag= 0

--- SFSBPOTOMC_T3.f01 (steady flow) ---

Flow Title=Flows
Program Version=5.07
Number of Profiles= 6
Profile Names=P100yr,P10yr,P25yr,P50yr,P500yr,P101yr
River Rch & RM=SFSBPOTOMC_T3,Main            ,2637
     197      94     131     163     285     239
River Rch & RM=SFSBPOTOMC_T3,Main            ,1752
     220     104     146     182     319     267
Boundary for River Rch & Prof#=SFSBPOTOMC_T3,Main            , 1
Up Type= 0
Dn Type= 3
Dn Slope=0.01327
Boundary for River Rch & Prof#=SFSBPOTOMC_T3,Main            , 2
Up Type= 0
Dn Type= 3
Dn Slope=0.01327
Boundary for River Rch & Prof#=SFSBPOTOMC_T3,Main            , 3
Up Type= 0
Dn Type= 3
Dn Slope=0.01327
Boundary for River Rch & Prof#=SFSBPOTOMC_T3,Main            , 4
Up Type= 0
Dn Type= 3
Dn Slope=0.01327
Boundary for River Rch & Prof#=SFSBPOTOMC_T3,Main            , 5
Up Type= 0
Dn Type= 3
Dn Slope=0.01327
Boundary for River Rch & Prof#=SFSBPOTOMC_T3,Main            , 6
Up Type= 0
Dn Type= 3
Dn Slope=0.01327
DSS Import GetInterval= 0
DSS Import GetPeak= 0
DSS Import FillOption= 0

--- SFSBPOTOMC_T3.g01 (geometry) ---

Geom Title=Geometry
Program Version=5.07

River Reach=SFSBPOTOMC_T3   ,Main
Reach XY= 30
     2480202.015      612438.715     2480239.852       612423.63
     2480265.804      612429.256     2480301.132      612467.151
     2480383.767      612521.433     2480397.562      612543.078
     2480445.868      612578.682      2480503.81      612603.052
     2480573.078      612651.823     2480635.454      612659.597
     2480662.095       612687.11     2480721.709      612720.881
     2480748.765      612725.867     2480780.474       612742.66
     2480800.073       612770.84     2480877.189      612787.425
     2480937.648      612812.781      2480973.56      612849.909
     2480998.339      612915.767     2481002.566       612972.19
     2480969.305      613064.798     2480898.235      613352.444
     2480889.856      613400.678     2480894.147      613473.925
     2480942.392      613566.889      2481097.88      613811.885
     2481183.557      613910.651     2481268.926      614034.383
     2481322.089      614100.027     2481540.597       614352.65

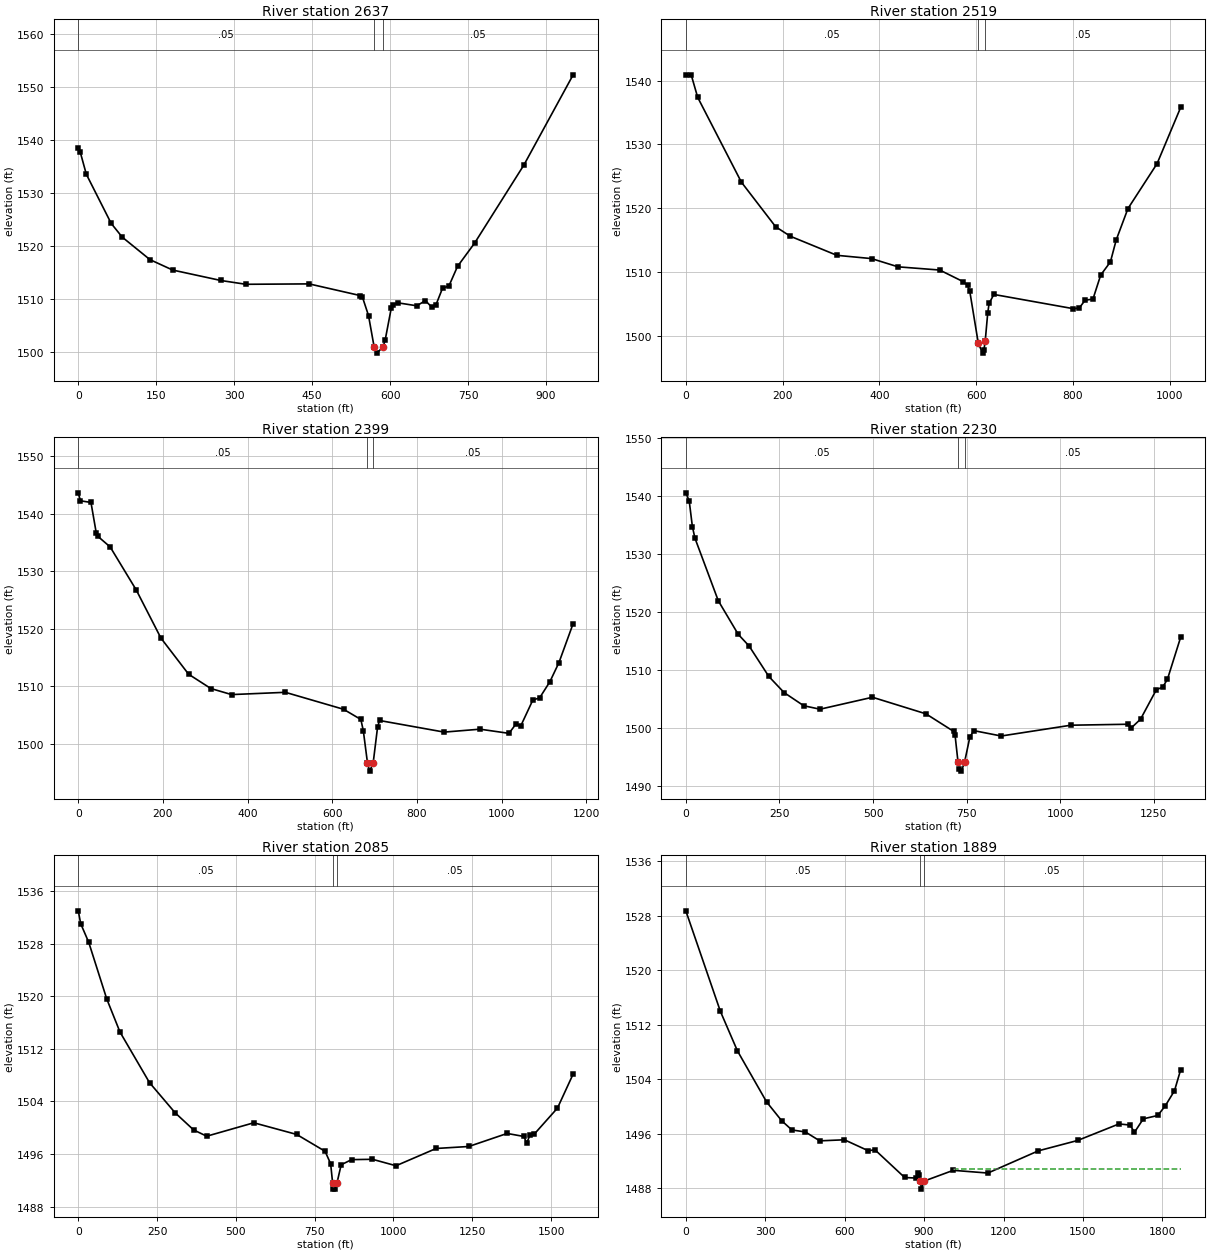
Type RM Length L Ch R = 1 ,2637    ,117.7,117.7,117.7
XS GIS Cut Line= 4
2479926.86870073612908.4670188092480225.33927801612474.934949098
2480223.95743836612380.9698531092480304.10413788 612059.00121538
#Sta/Elev= 30
       01538.4883.9205671537.63915.425241533.51263.266491524.21884.470731521.624
137.89011517.365181.59681515.396274.28051513.422322.42961512.704444.17381512.779
542.38671510.575546.38711510.383558.38841506.803  569.31 1500.82574.39021499.693
586.39151500.874590.39191502.132602.39321508.309606.39361508.831614.39451509.209
 651.313 1508.64667.80131509.614680.16751508.383688.41161508.878700.77781511.954
 713.1441512.389729.63231516.083762.60881520.498857.41641535.259952.11021552.294
#Mann= 3 , 0 , 0
       0     .05       0  569.31    .045       0586.3915     .05       0
Bank Sta=569.31,586.3915
XS Rating Curve= 0 ,0
Exp/Cntr(USF)=0,0
Exp/Cntr=0.3,0.1

Type RM Length L Ch R = 1 ,2519    ,120.2,120.2,120.2
XS GIS Cut Line= 4
2479951.73502792612969.6335426892480288.90390177612534.354053915
  2480342.795648612440.3889579252480375.95979952612078.346970437
#Sta/Elev= 30
       01540.90411.447241540.81524.511121537.378114.78181524.108 185.6171517.125
 215.9751515.639312.10851512.653383.76771512.141   438.6 1510.85524.6143 1510.35
573.02861508.532 582.2511507.961586.71281507.027   604.2 1498.94 613.0871497.345
616.01751497.887618.6123 1499.23623.75161503.573626.65231505.141636.53081506.529
801.00461504.297813.05481504.417 825.1051505.643841.17211505.791 857.2391509.566
877.29411511.623 889.3731515.082913.47351519.963973.72471527.0051022.4721535.805
#Mann= 3 , 0 , 0
       0     .05       0   604.2    .045       0618.6123     .05       0
Bank Sta=604.2,618.6123
XS Rating Curve= 0 ,0
Exp/Cntr(USF)=0,0
Exp/Cntr=0.3,0.1

Type RM Length L Ch R = 1 ,2399    ,169.1,169.1,169.1
XS GIS Cut Line= 4
 2479983.5173398613092.6172712632480357.99588411612644.901225667
2480468.54305586612458.352873335 2480428.4697061612092.165366906
#Sta/Elev= 30
       01543.6365.0308571542.25229.969271541.96442.438481536.66946.111341536.081
75.257111534.235136.97941526.743195.1963 1518.39260.64961512.104313.03621509.624
362.06811508.567 489.0931508.962626.56851506.015667.44161504.245673.28061502.285
  683.09  1496.7 688.3091495.263   696.6 1496.71706.90731502.891711.55691504.063
864.36541502.045948.86681502.5551017.273 1501.831033.3681503.405 1045.441503.161
1073.6891507.6181089.7031507.9961113.8461510.7861135.3481514.1211168.8981520.909
#Mann= 3 , 0 , 0
       0     .05       0  683.09    .045       0   696.6     .05       0
Bank Sta=683.09,696.6
XS Rating Curve= 0 ,0
Exp/Cntr(USF)=0,0
Exp/Cntr=0.3,0.1

Type RM Length L Ch R = 1 ,2230    ,144.4,144.4,144.4
XS GIS Cut Line= 4
2480040.17276532613158.9455743152480527.96216068612698.792971896
2480601.19966197612539.8814125022480447.81546116612089.401687612
#Sta/Elev= 30
       01540.5679.0351341539.18617.567331534.72924.495371532.73786.747211521.971
139.98071516.193169.12671514.173221.58951508.944 262.3941506.167314.85681503.897
358.39161503.301498.44071505.359641.29231502.502714.81321499.495718.92121498.864
   726.91494.166729.88771493.081735.91751492.636  744.23 1494.15758.5605 1498.53
769.0813 1499.61842.24331498.685  1028.31500.5451180.4191500.711 1188.871500.041
1214.2231501.5771256.4781506.656 1273.381507.1081286.057 1508.451321.4341515.704
#Mann= 3 , 0 , 0
       0     .05       0   726.9    .045       0  744.23     .05       0
Bank Sta=726.9,744.23
XS Rating Curve= 0 ,0
Exp/Cntr(USF)=0,0
Exp/Cntr=0.3,0.1

Type RM Length L Ch R = 1 ,2085    ,196.5,196.5,196.5
XS GIS Cut Line= 4
2480098.68959899613257.6949820582480638.91497535612787.604128242
2480758.33321644612529.8123696982480492.95934735612025.602018428
#Sta/Elev= 30
       0 1532.97 7.697341531.01433.214451528.17290.214041519.589132.23451514.552
226.0103 1506.85307.61181502.253 365.9381499.665407.46531498.711556.82391500.752
692.83341498.981783.03171496.417800.66511494.521806.91181491.612809.48181490.743
812.93731490.667820.39681491.525834.02641494.369867.16641495.151933.44651495.201
 1008.05 1494.221135.3541496.8471239.0071497.1491360.6251499.1311413.7361498.672
 1422.621497.6381432.9481498.8881446.313 1499.01 1520.351502.989 1570.01 1508.16
#Mann= 3 , 0 , 0
       0     .05       0806.9118    .045       0820.3968     .05       0
Bank Sta=806.9118,820.3968
XS Rating Curve= 0 ,0
Exp/Cntr(USF)=0,0
Exp/Cntr=0.3,0.1

Type RM Length L Ch R = 1 ,1889    ,136.6,136.6,136.6
XS GIS Cut Line= 4
2480142.28673462613305.0831729672480824.67668371612846.365484969
2480938.40834189612548.7676460622480521.39226189 611951.67644061
#Sta/Elev= 30
       01528.748130.68591513.978195.02071508.185305.06531500.699362.03451497.939
400.59261496.584 451.541 1496.29505.82241494.984599.0311 1495.14689.7784 1493.52
713.74941493.692826.53281489.604868.78081489.523877.34511490.213881.62731490.009
   884.71489.157890.19151487.897   899.11489.0631010.0921490.6561140.8291490.257
1331.5321493.5181479.7681495.0381636.0351497.4661678.1491497.3021694.4441496.229
1727.9611498.2131782.5411498.707 1810.881500.117 1845.741502.3381869.1291505.429
#Mann= 3 , 0 , 0
       0     .05       0   884.7    .045       0   899.1     .05       0
#XS Ineff= 2 , 0
                            1013         1490.87
Permanent Ineff=
       F       F
Bank Sta=884.7,899.1
XS Rating Curve= 0 ,0
Exp/Cntr(USF)=0,0
Exp/Cntr=0.3,0.1

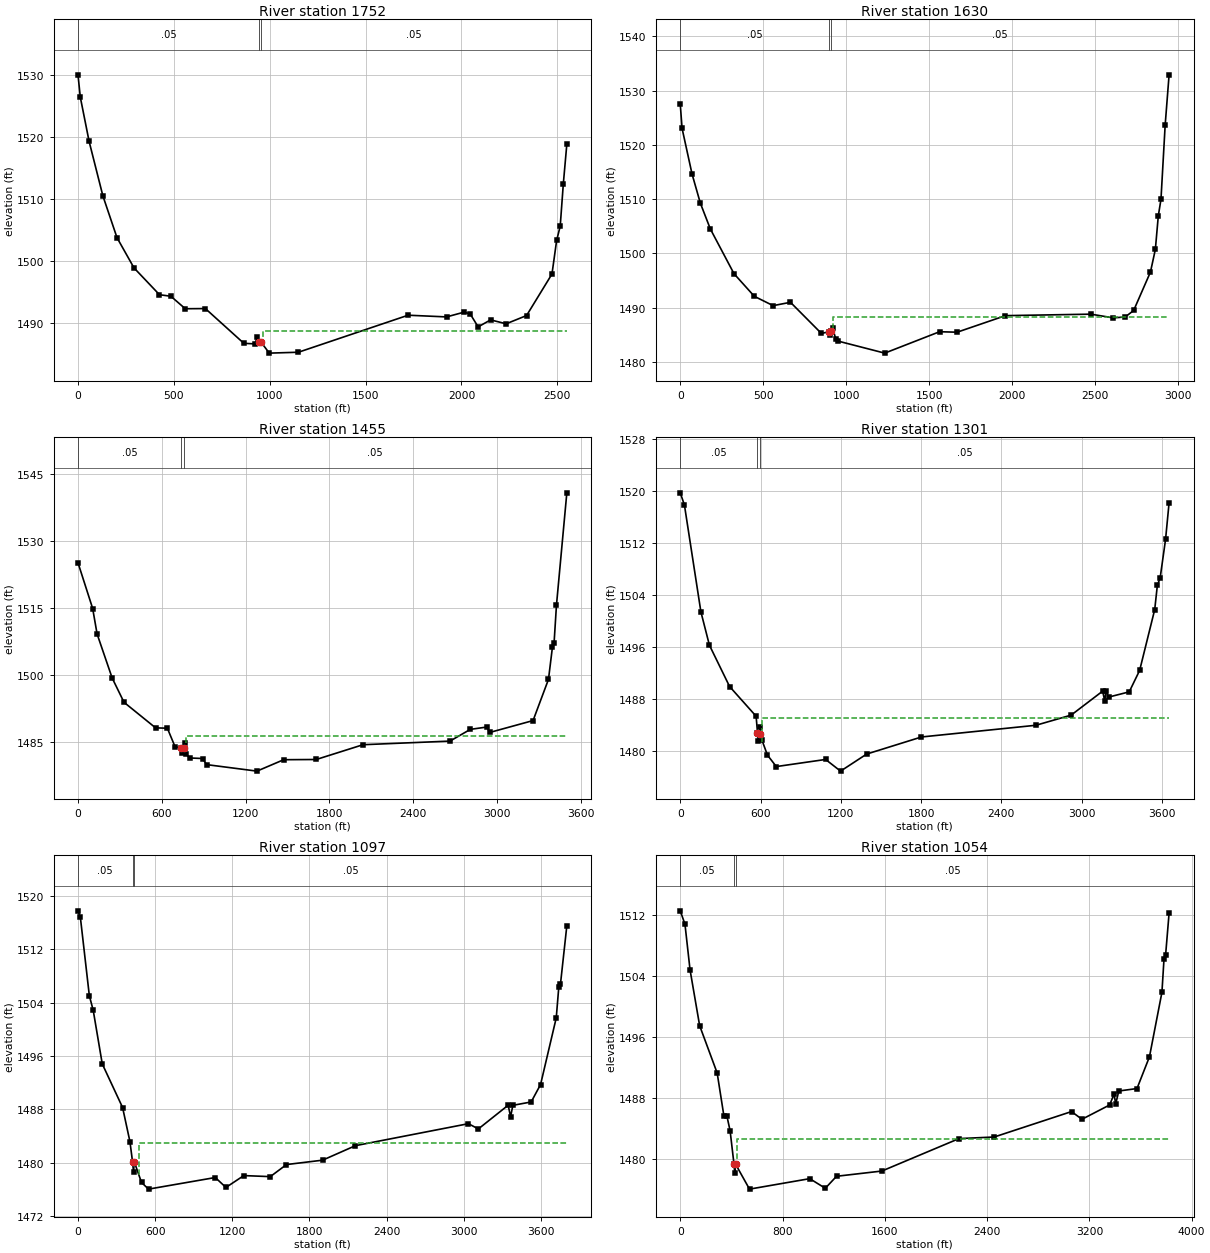
Type RM Length L Ch R = 1 ,1752    ,122.3,122.3,122.3
XS GIS Cut Line= 5
 2480193.4659808613386.5908613312480826.57221135612931.664228605
2481018.02050262612810.3504598792481145.12072983612744.183538046
2480663.66594171 611429.72324256
#Sta/Elev= 30
       01530.08812.165921526.48158.023571519.354129.6761 1510.59203.52371503.827
292.18411498.959424.88481494.637484.28171494.389559.59161492.375664.39791492.402
865.04631486.796923.03791486.711936.07791487.881  943.85 1487.09  952.33 1487.09
997.68931485.2181149.5441485.3621721.7431491.3311921.9581491.0572012.9361491.819
2045.4941491.531 2086.871489.4512151.9911490.5812232.9281489.9452339.4251491.277
2471.9511497.9752496.2061503.3782514.9141505.6952531.1191512.5222549.4031518.914
#Mann= 3 , 0 , 0
       0     .05       0  943.85    .045       0  952.33     .05       0
#XS Ineff= 2 , 0
                          966.08         1488.72
Permanent Ineff=
       F       F
Bank Sta=943.85,952.33
XS Rating Curve= 0 ,0
Exp/Cntr(USF)=0,0
Exp/Cntr=0.3,0.1

Type RM Length L Ch R = 1 ,1630    ,175.2,175.2,175.2
XS GIS Cut Line= 5
2480257.91392044 613449.143273332480879.64698516612982.843474787
2481057.82658298 612944.932922062481315.00938906 612856.23776009
2480770.82900224611232.508207528
#Sta/Elev= 30
       0 1527.52 11.03891523.028 71.03891514.633121.03891509.265181.03891504.527
 323.7541496.276446.03891492.115559.34541490.397 663.7541491.012849.85581485.287
   893.21485.553898.9303    1485   907.41485.688 919.3781486.188935.73611484.289
951.71391483.8571231.3821481.6531561.8581485.5941667.3251485.5041958.4121488.555
 2473.091488.8272608.0871488.1442679.8041488.3132730.4281489.5052831.6761496.587
2861.2071500.7592878.8641506.9142894.9561509.9552920.2681523.6652943.8741532.893
#Mann= 3 , 0 , 0
       0     .05       0   893.2    .045       0   907.4     .05       0
#XS Ineff= 2 , 0
                          918.14         1488.39
Permanent Ineff=
       F       F
Bank Sta=893.2,907.4
XS Rating Curve= 0 ,0
Exp/Cntr(USF)=0,0
Exp/Cntr=0.3,0.1

Type RM Length L Ch R = 1 ,1455    ,153.2,153.2,153.2
XS GIS Cut Line= 5
2480347.00371935613521.1733235122480832.25879426 613126.90357515
2481061.61763825613121.2169922412481466.82478667613076.731551854
2481015.74334553610886.213628716
#Sta/Elev= 30
       01525.145105.11141514.897136.82761509.188244.66261499.337329.51511493.902
555.48141488.181639.72751488.105695.7448 1483.88   740.6 1483.75747.76071482.656
   755.71483.729763.7657 1484.79775.76931482.241799.77671481.445892.01671481.322
920.18491479.9571280.8671478.4991472.4681481.0541705.2521481.1022040.1341484.412
2662.5811485.2212808.2031487.8472926.7321488.3682946.7661487.1543257.1451489.817
3367.4111499.0363395.9981506.3093407.623 1507.253424.5861515.6383498.7881540.787
#Mann= 3 , 0 , 0
       0     .05       0   740.6    .045       0   755.7     .05       0
#XS Ineff= 2 , 0
                          772.11         1486.42
Permanent Ineff=
       F       F
Bank Sta=740.6,755.7
XS Rating Curve= 0 ,0
Exp/Cntr(USF)=0,0
Exp/Cntr=0.3,0.1

Type RM Length L Ch R = 1 ,1301    ,204.6,204.6,204.6
XS GIS Cut Line= 5
2480472.10854335613608.3675947842480807.61693498613270.963675513
2480968.73678407613272.8592031492481568.03505174613112.878075094
2481179.94542185610748.901745204
#Sta/Elev= 30
       01519.70131.19288 1517.83154.38921501.368217.86981496.243368.74671489.873
566.95721485.295   577.21482.785582.95831481.479   592.51482.638598.95941483.566
610.96021481.594651.45251479.316717.69371477.545 1086.161478.6411197.9421476.844
1393.0191479.4721802.4271482.1022657.7241483.9062921.2051485.471 3156.311489.163
3171.6671487.6733182.1121489.2353200.8991488.2443354.9341489.0513432.8111492.356
 3545.451501.7253565.1241505.4623586.0151506.5963626.5211512.5423652.8581518.181
#Mann= 3 , 0 , 0
       0     .05       0   577.2    .045       0   592.5     .05       0
#XS Ineff= 2 , 0
                          614.62         1485.08
Permanent Ineff=
       F       F
Bank Sta=577.2,592.5
XS Rating Curve= 0 ,0
Exp/Cntr(USF)=0,0
Exp/Cntr=0.5,0.3

Type RM Length L Ch R = 1 ,1097    ,43.2,43.2,43.2
XS GIS Cut Line= 5
2480493.76494659613621.9244084392480835.07933938613472.685726574
2480931.80811466613474.0675662212481719.85044935613138.180641362
2481274.84654533610701.903451653
#Sta/Elev= 30
       0 1517.7918.532311516.81688.382821505.045118.47341502.862188.79291494.825
347.04231488.274404.18431483.154   424.21480.154432.18721478.635  437.38 1480.15
494.18751477.031548.76641476.0311068.1481477.7731150.7641476.2821289.9061478.063
1495.9511477.9061621.9161479.7181902.5691480.3752158.2711482.5533037.0331485.851
3114.2911485.0613346.063 1488.623365.0691486.9043382.6581488.6063524.975 1489.11
3598.1661491.7253720.1511501.729 3739.831506.3193752.681 1506.743802.4791515.551
#Mann= 3 , 0 , 0
       0     .05       0   424.2    .045       0  437.38     .05       0
#XS Ineff= 2 , 0
                          474.63          1482.9
Permanent Ineff=
       F       F
Bank Sta=424.2,437.38
XS Rating Curve= 0 ,0
Exp/Cntr(USF)=0,0
Exp/Cntr=0.5,0.3

Type RM Length L Ch R = 1 ,1054    ,90,90,90
XS GIS Cut Line= 5
2480521.40173953613670.288796081 2480824.0246222 613527.95931245
2480956.68122831613504.4680384522481748.76766794 613145.40994601
2481310.14209554610699.772052969
#Sta/Elev= 30
       0 1512.49  36.8471510.74376.629851504.755151.77531497.431288.80511491.226
341.24731485.624365.62071485.528389.99411483.658  420.36 1479.28426.5542 1478.07
   433.11479.261541.67741476.0031012.8181477.3761134.5691476.1161222.4041477.688
1577.0391478.3752180.0571482.6272455.7231482.8373060.3681486.1713141.9391485.162
3358.5261487.0373392.9851488.4643405.7931487.1733430.1761488.869 3572.41 1489.19
3669.9421493.3553767.4741501.8083783.7291506.192 3795.921506.6383823.4721512.192
#Mann= 3 , 0 , 0
       0     .05       0  420.36    .045       0   433.1     .05       0
#XS Ineff= 2 , 0
                          443.75         1482.63
Permanent Ineff=
       F       F
Bank Sta=420.36,433.1
XS Rating Curve= 0 ,0
Exp/Cntr(USF)=0,0
Exp/Cntr=0.5,0.3

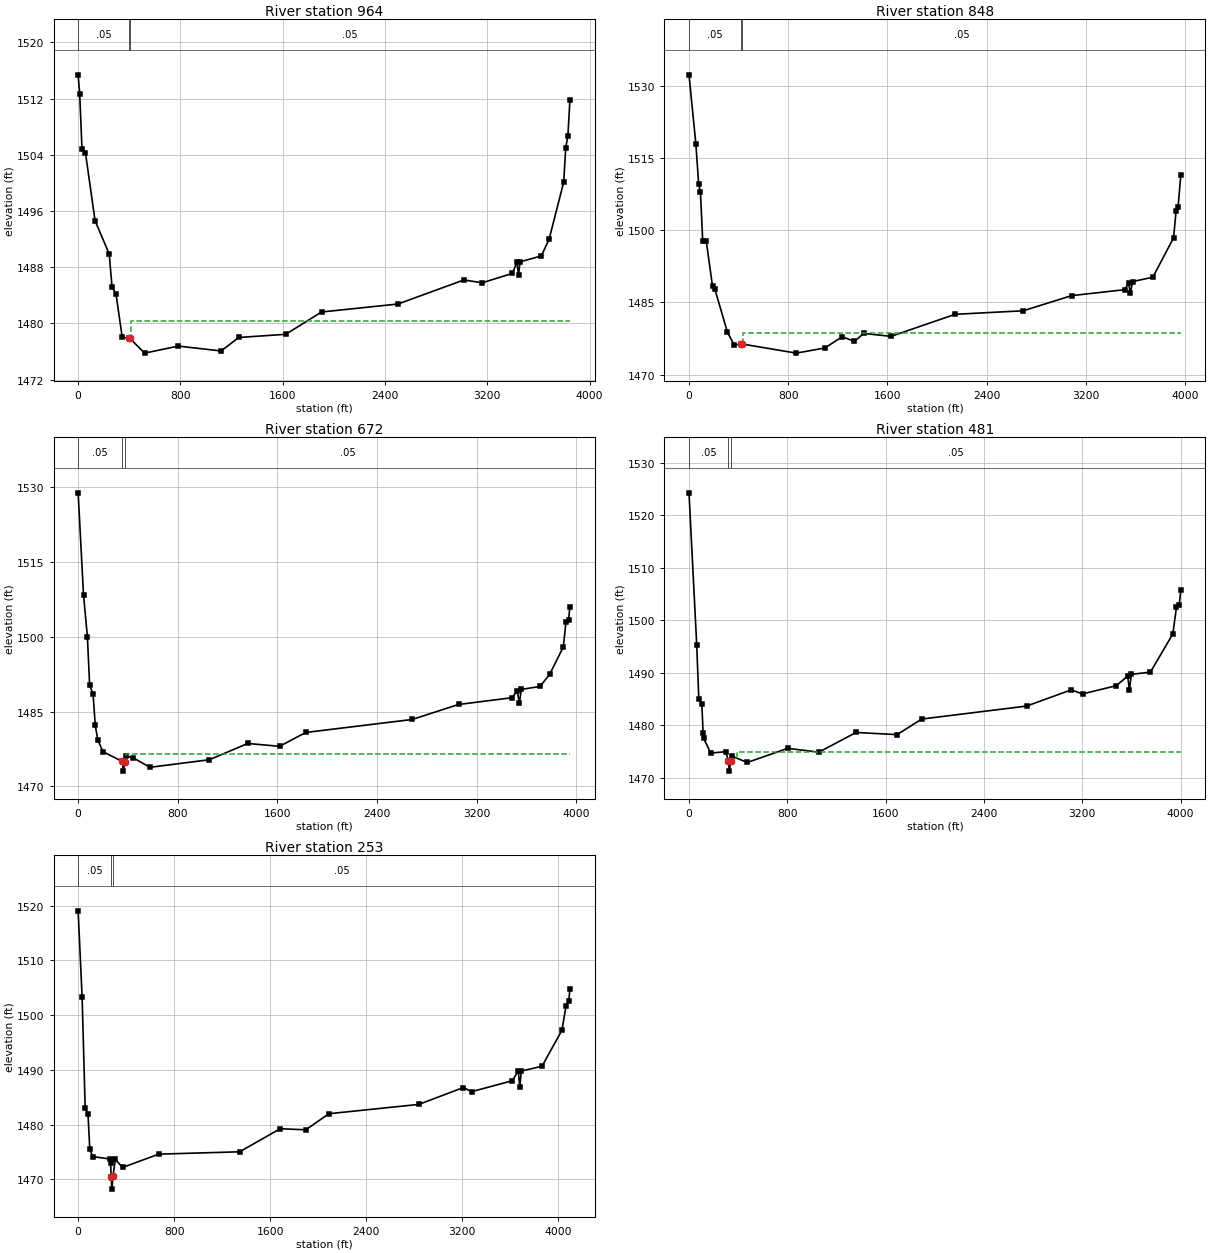
Type RM Length L Ch R = 1 ,964     ,115,115,115
XS GIS Cut Line= 5
2480594.63924082613762.8720524232480909.69868031613615.015210205
2481343.59632944613391.157187407 2481788.5288435 613145.40994601
2481348.30273903610682.651178372
#Sta/Elev= 30
       01515.37912.094481512.71830.138121504.86757.203571504.291132.38541494.607
243.1388 1489.87265.23171485.163296.16181484.182344.76611478.027   395.31477.862
  405.13 1477.85520.24361475.759782.39151476.7621118.6111476.0681255.6981477.988
1623.4291478.4381903.8031481.6152501.124 1482.753017.1761486.1793159.3951485.769
3395.906 1487.113431.6431488.6943444.1671486.9113456.023 1488.753622.6231489.596
3683.5741491.9943797.3491500.0913813.6031505.0123830.2531506.7133846.3541511.854
#Mann= 3 , 0 , 0
       0     .05       0   395.3    .045       0  405.13     .05       0
#XS Ineff= 2 , 0
                          417.01         1480.28
Permanent Ineff=
       F       F
Bank Sta=395.3,405.13
XS Rating Curve= 0 ,0
Exp/Cntr(USF)=0,0
Exp/Cntr=0.3,0.1

Type RM Length L Ch R = 1 ,848     ,176.5,176.5,176.5
XS GIS Cut Line= 5
2480651.29466634613899.6741774672480940.09915254613729.707900898
 2481472.1074166613443.6670939892481849.97793301613141.795293686
2481386.04186212610641.398816951
#Sta/Elev= 30
       01532.24555.057811517.94778.264291509.51192.188181507.955110.75341497.662
138.60121497.816189.65541488.344208.22061487.781309.87941478.801365.35991476.121
   420.81476.383427.74591476.363864.92581474.4691096.1031475.5411235.1771477.875
1334.321 1476.911408.4051478.563 1629.15 1477.95 2145.821482.5262694.2931483.259
3085.5911486.4053512.7591487.6413545.3211488.999 3557.511486.8693577.8521489.329
3740.0911490.2243907.3811498.4083927.7231504.0053943.3821504.7063965.8551511.459
#Mann= 3 , 0 , 0
       0     .05       0   420.8    .045       0427.7459     .05       0
#XS Ineff= 2 , 0
                          437.32         1478.64
Permanent Ineff=
       F       F
Bank Sta=420.8,427.7459
XS Rating Curve= 0 ,0
Exp/Cntr(USF)=0,0
Exp/Cntr=0.3,0.1

Type RM Length L Ch R = 1 ,672     ,191.4,191.4,191.4
XS GIS Cut Line= 5
2480833.69749973614059.9675765072481056.17368288613873.419224176
2481175.01189252613796.0362039492481871.66584696 613145.40994601
2481405.17685698610623.005448917
#Sta/Elev= 30
       01528.89343.127961508.44274.44863    150092.366011490.374119.95961488.515
137.79511482.217157.97041479.324199.73131476.949   355.21474.991363.40391473.058
  375.73 1474.97384.09841476.036 439.6881475.767577.10521473.8231055.0261475.348
1362.2241478.6071618.3361478.0311827.7461480.8132682.5491483.4183055.7481486.428
3486.9381487.7933527.0541489.1863544.2191486.7153560.1591489.4513710.6691490.047
3787.957  1492.53897.812    1498 3918.411503.0123939.0081503.3773950.5541506.084
#Mann= 3 , 0 , 0
       0     .05       0   355.2    .045       0  375.73     .05       0
#XS Ineff= 2 , 0
                          387.35         1476.55
Permanent Ineff=
       F       F
Bank Sta=355.2,375.73
XS Rating Curve= 0 ,0
Exp/Cntr(USF)=0,0
Exp/Cntr=0.3,0.1

Type RM Length L Ch R = 1 ,481     ,227.7,227.7,227.7
XS GIS Cut Line= 6
2480981.55434195614194.0060222572481202.64868545614015.748707807
2481476.25293554613749.0536559542481828.29001907 613217.70299249
2481915.04167484 613109.263422772481413.14778844610600.146455529
#Sta/Elev= 30
       01524.32362.799871495.28479.867781484.978104.2926  1484.1114.5689 1478.62
119.67541477.503176.22671474.691300.89641474.977  319.55 1473.11328.82581471.258
  339.03 1473.14346.90951474.139474.05891472.906803.03011475.6031056.182 1474.87
1358.6281478.6271692.7591478.2221893.4791481.188 2746.041483.6613109.092 1486.75
3202.0421485.9823476.2231487.5533569.1651489.3943582.7621486.687  3598.61489.718
3753.6111490.1253936.288 1497.433965.7321502.5033987.2771502.8594001.1641505.778
#Mann= 3 , 0 , 0
       0     .05       0  319.55    .045       0  339.03     .05       0
#XS Ineff= 2 , 0
                          386.88         1474.83
Permanent Ineff=
       F       F
Bank Sta=319.55,339.03
XS Rating Curve= 0 ,0
Exp/Cntr(USF)=0,0
Exp/Cntr=0.3,0.1

Type RM Length L Ch R = 1 ,253     ,,,
XS GIS Cut Line= 5
2481151.52061852614333.5718265942481329.77793297614207.824418726
 2481516.3262853614025.4215853352481994.56402597613123.722032066
2481418.88590724 610587.06968588
#Sta/Elev= 30
       01519.06933.316581503.22958.773451482.96382.267591481.974 96.95291475.568
121.42841474.151265.25421473.708270.97571472.979   275.2 1470.51281.03741468.202
  290.69 1470.52310.00631473.628370.54711472.162672.08241474.5941346.4461475.027
1685.1541479.2381898.4431479.0482091.2231481.9862840.8241483.688  3211.91486.771
3282.1041486.0213621.1631488.0183669.896 1489.843682.6881486.7923694.9941489.781
3867.4731490.6644034.2861497.2494067.7171501.6364091.1181502.609 4100.88 1504.84
#Mann= 3 , 0 , 0
       0     .05       0   275.2    .045       0  290.69     .05       0
Bank Sta=275.2,290.69
XS Rating Curve= 0 ,0
Exp/Cntr(USF)=0,0
Exp/Cntr=0.3,0.1
LCMann Table=0

Chan Stop Cuts=-1
Use User Specified Reach Order=0
Composite Channel Slope=5